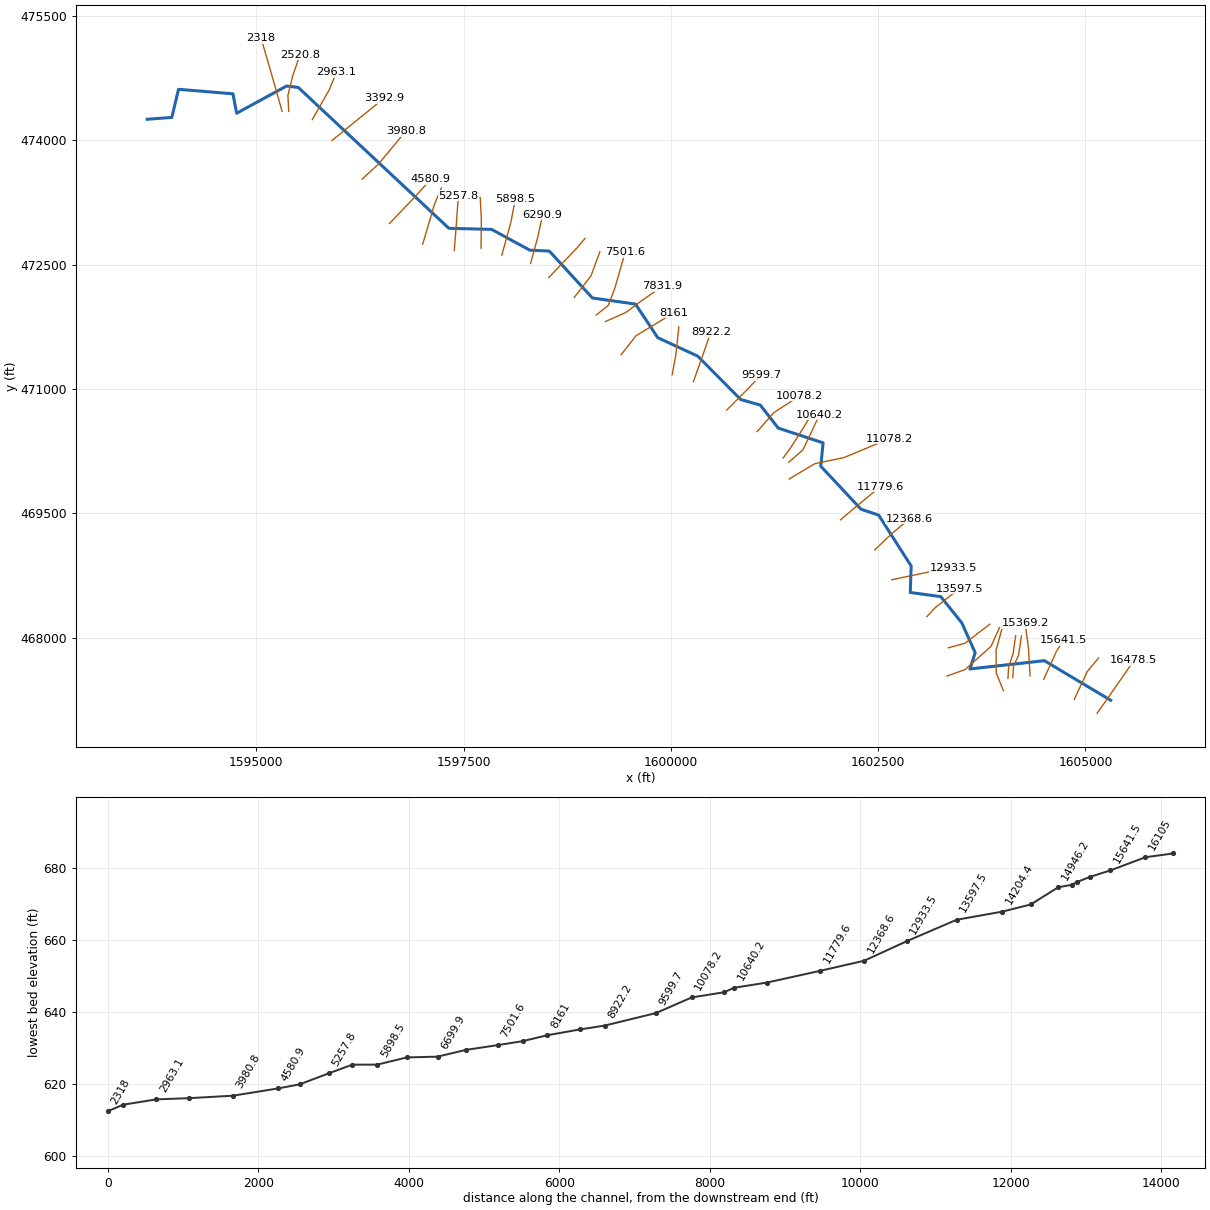
--- BowenCr.prj (project) ---

Proj Title=BowenCr
Current Plan=p01
Default Exp/Contr=0,0
English Units
Geom File=g01
Flow File=f01
Plan File=p01
BEGIN DESCRIPTION:
END DESCRIPTION:
DSS Export Rating Curves= 0
DSS Export Rating Curve Sorted= 0
DSS Export Volume Flow Curves= 0
DXF OffsetX= 0
DXF OffsetY= 0
DXF ScaleX= 0
DXF ScaleY= 0

--- BowenCr.p01 (plan) ---

Plan Title=Floodplain
Program Version=4.00
Geom File=g01
Flow File=f01
K Sum by GR=0
Std Step Tol=0.01
Critical Tol=0.01
Num of Std Step Trials=20
Max Error Tol=0.3
Flow Tol Ratio=0.001
Split Flow NTrial=30
Split Flow Tol=0.02
Split Flow Ratio=0.02
Log Output Level=0
Friction Slope Method=1
Unsteady Friction Slope Method=2
Unsteady Bridges Friction Slope Method=1
Global Log Level=0
CheckData=False
Run HTab=0
Run UNet=0
Run PostProcess=0
UNET Theta=0
UNET Theta Warmup=0
UNET ZTol=0
UNET ZSATol=0
UNET MxIter=0
UNET MaxInSteps=0
UNET DtIC=0
UNET DtMin=0
UNET MaxCRTS=0
UNET WFStab=0
UNET SFStab=0
UNET WFX=0
UNET SFX=0
UNET DSS MLevel=0
UNET DZMax Abort=0
UNET Convert EG Bridges=0
UNET Use Existing IB Tables=0
UNET Froude Limit=0
UNET Froude Power=0
Write IC File=0
Echo Input=False
Echo Output=False
Write Detailed=0

--- BowenCr.f01 (steady flow) ---

Flow Title=NFF Regression Equation
Program Version=4.10
Number of Profiles= 1
Profile Names=P100yr
River Rch & RM=BowenCr,Main            ,16478.5
     851
River Rch & RM=BowenCr,Main            ,16105
     987
River Rch & RM=BowenCr,Main            ,14946.2
    1013
River Rch & RM=BowenCr,Main            ,14204.4
    1093
River Rch & RM=BowenCr,Main            ,12933.5
    1104
River Rch & RM=BowenCr,Main            ,11078.2
    1192
River Rch & RM=BowenCr,Main            ,10640.2
    1416
River Rch & RM=BowenCr,Main            ,7501.6
    1490
River Rch & RM=BowenCr,Main            ,7077.8
    1648
River Rch & RM=BowenCr,Main            ,4580.9
    1705
River Rch & RM=BowenCr,Main            ,48.8
    1835
Boundary for River Rch & Prof#=BowenCr,Main            , 1
Up Type= 0
Dn Type= 3
Dn Slope=0.0054
DSS Import GetInterval= 0
DSS Import GetPeak= 0
DSS Import FillOption= 0

--- BowenCr.g01 (geometry) ---

Geom Title=USGS 10m DEM
Program Version=4.10

River Reach=BowenCr         ,Main
Reach XY= 30
     1605304.114      467246.009     1604504.006      467723.212
      1603606.61      467623.385     1603669.978      467818.698
     1603507.652      468180.243     1603254.634      468495.657
     1602886.992      468545.694     1602897.409      468865.573
     1602505.048       469479.18     1602292.795      469549.996
      1601807.46       470068.49     1601835.595      470349.844
     1601293.817      470528.691     1601077.841      470805.835
     1600842.428      470872.441     1600324.373      471395.358
     1599841.734      471618.275     1599572.984       472023.83
     1599053.713      472096.921     1598533.748      472662.893
     1598298.505      472674.177     1597836.699      472925.046
      1597322.81      472937.198     1595506.113      474636.157
       1595365.4      474653.687     1594762.914      474325.393
     1594718.485      474559.541     1594061.916      474614.021
     1593980.995      474274.704     1593685.035       474252.91

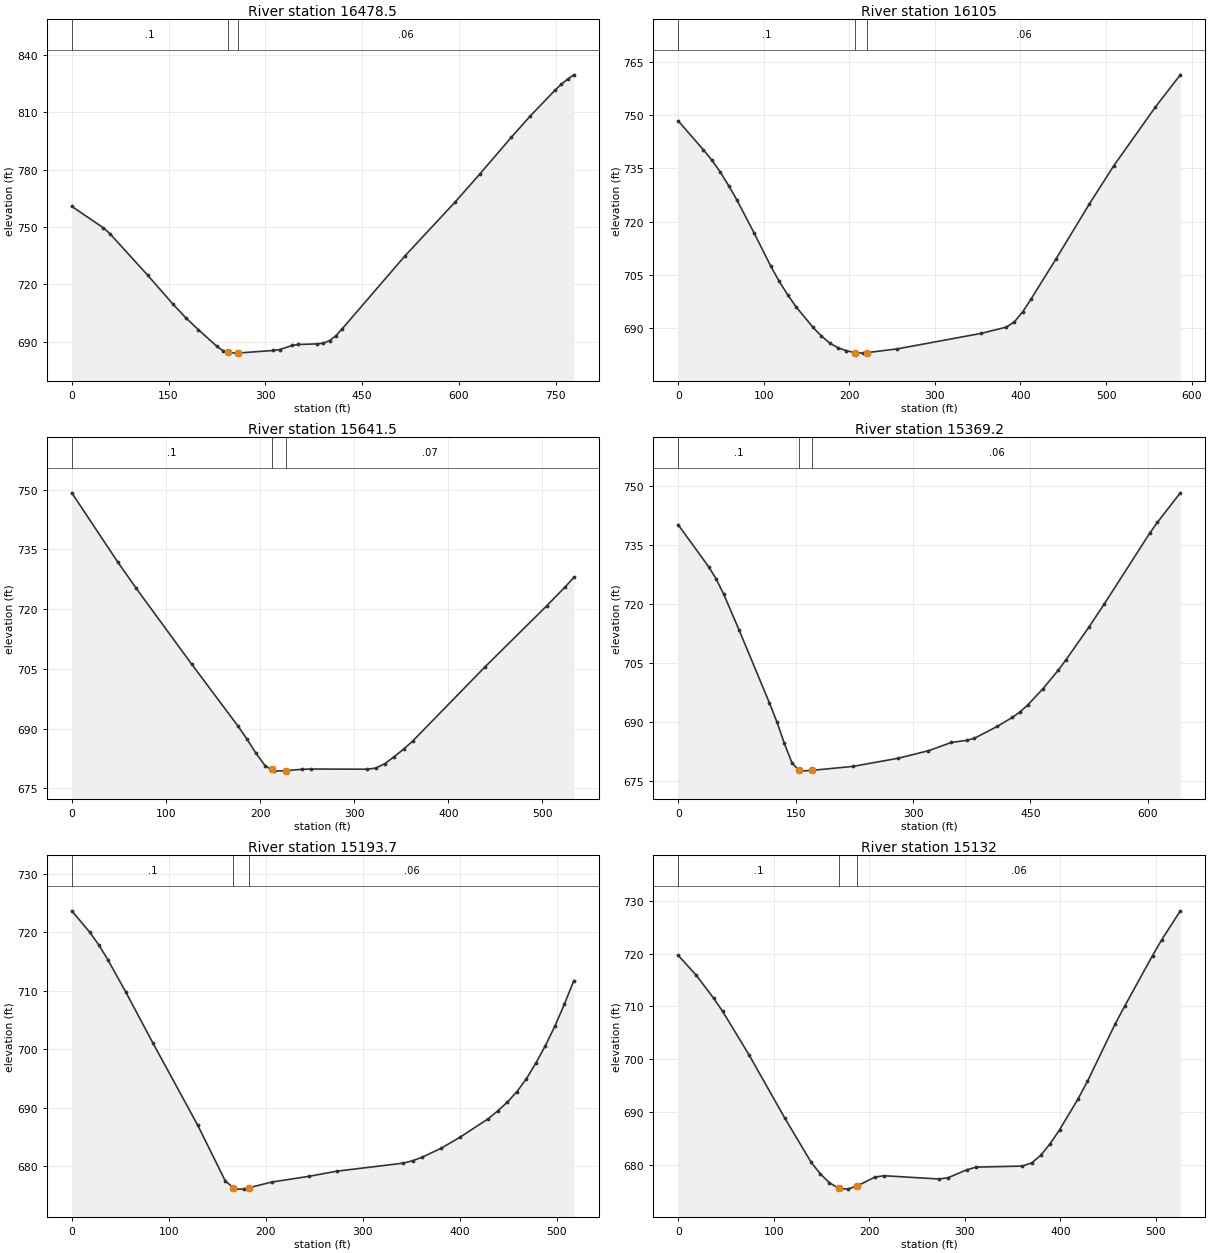
Type RM Length L Ch R = 1 ,16478.5 ,370,373.5,376.7
XS GIS Cut Line= 3
     1605139.043       467087.64      1605224.98      467207.431
     1605584.355       467725.66
#Sta/Elev= 30
       0  760.88    49.1  749.59      59  746.62   117.9  724.74   157.1  709.59
   176.5  702.66   195.9  696.42     225  687.57   234.8  685.23   242.2  684.46
   254.2  684.06   257.2  684.11   312.4  685.45   322.1   685.9   341.5  688.07
   351.2  688.58   380.3   688.9     390  689.29   399.7  690.64   409.4  693.21
   419.1   696.8   516.1  734.84   593.7  762.98   632.5  777.85     681  796.93
   710.2  808.03     749  821.68   758.7  824.76   768.4  827.46   778.1   829.7
#Mann= 3 , 0 , 0
       0      .1       0   242.2    .045       0   257.2     .06       0
Bank Sta=242.2,257.2
XS Rating Curve= 0 ,0
Exp/Cntr=0.3,0.1

Type RM Length L Ch R = 1 ,16105   ,463.2,463.4,463.5
XS GIS Cut Line= 3
     1604863.869      467255.174     1605021.855      467593.716
     1605159.008       467756.91
#Sta/Elev= 30
       0  748.37    29.5  740.21    39.3  737.32    49.2  733.95      59  730.11
    68.8  726.01    88.5   716.9   108.1   707.5     118  703.22   127.8  699.46
   137.6  696.06   157.3  690.31   167.1  687.86     177  685.83   186.8   684.5
   196.6  683.68   206.2  683.13   216.3  682.99   221.2  683.15   255.6  684.17
   353.9  688.54   383.3   690.3     393  691.83   402.7  694.65   412.4  698.24
   441.4  709.46   480.2  724.87   509.2  735.81   557.7  752.28   586.8  761.34
#Mann= 3 , 0 , 0
       0      .1       0   206.2    .045       0   221.2     .06       0
Bank Sta=206.2,221.2
XS Rating Curve= 0 ,0
Exp/Cntr=0.3,0.1

Type RM Length L Ch R = 1 ,15641.5 ,261.3,272.3,283.2
XS GIS Cut Line= 3
     1604496.682      467499.098     1604650.762       467837.64
     1604739.737      467972.188
#Sta/Elev= 23
       0   749.2    48.9  731.81    68.5  725.21   127.2  706.25   176.2  690.77
     186  687.42   195.8  683.78   205.6  680.62   212.2  679.75   215.3  679.34
   227.2  679.47   244.7   679.8   254.5  679.87   313.2  679.82     323   680.1
   332.8  681.25   342.6  682.99   352.4  684.84   362.2  686.91   438.4  705.38
   504.8  720.91   523.8  725.52   533.3  727.96
#Mann= 3 , 0 , 0
       0      .1       0   212.2    .045       0   227.2     .07       0
Bank Sta=212.2,227.2
XS Rating Curve= 0 ,0
Exp/Cntr=0.3,0.1

Type RM Length L Ch R = 1 ,15369.2 ,187.3,175.5,163.2
XS GIS Cut Line= 3
     1604331.751      467540.331      1604312.22      467878.872
     1604270.987      468178.351
#Sta/Elev= 30
       0   740.1    38.8  729.47    48.4  726.39    58.1  722.47    77.5   713.5
   116.3  694.96     126  690.07   135.6  684.55   145.3  679.62  154.22  677.69
     155  677.53   171.4  677.74   222.8  678.72     281   680.8   319.7  682.72
   348.9  684.81   368.4  685.36   378.1  685.85   407.4  688.88   426.9  691.19
   436.6  692.57   446.4  694.31   465.9  698.46   485.4  703.15   495.1  705.75
   524.4  714.05   543.9  719.89   602.4     738   612.2  740.75   641.4  748.23
#Mann= 3 , 0 , 0
       0      .1       0  154.22    .045       0   171.4     .06       0
Bank Sta=154.22,171.4
XS Rating Curve= 0 ,0
Exp/Cntr=0.3,0.1

Type RM Length L Ch R = 1 ,15193.7 ,61.9,61.8,64
XS GIS Cut Line= 4
     1604123.418      467518.629     1604132.099      467657.518
     1604192.862      467787.726     1604227.585      468019.931
#Sta/Elev= 30
       0  723.66    18.6  719.99    27.8  717.84    37.1  715.33    55.7  709.77
    83.5   701.1   129.9  686.98   158.3  677.46  166.62  676.31   167.9  676.07
   177.5  676.07   183.2  676.33   206.2  677.28   244.5  678.26   273.3  679.14
   341.6  680.51   351.3  680.92   361.1  681.52   380.7  683.05   400.2  684.94
   429.6  688.14   439.4  689.48   449.2  690.98   458.9  692.74   468.7  694.95
   478.5  697.64   488.3  700.62   498.1  703.97   507.8  707.68   517.6  711.74
#Mann= 3 , 0 , 0
       0      .1       0  166.62    .045       0   183.2     .06       0
Bank Sta=166.62,183.2
XS Rating Curve= 0 ,0
Exp/Cntr=0.3,0.1

Type RM Length L Ch R = 1 ,15132   ,175,185.8,194.5
XS GIS Cut Line= 4
     1604064.824      467509.949     1604073.505      467648.837
     1604125.588      467802.917      1604158.14      468024.272
#Sta/Elev= 30
       0  719.67    18.6  715.96    37.1  711.54    46.4  709.08    74.2  700.78
   111.3  688.89   139.2  680.42   148.7  678.25   158.3  676.55   167.9  675.51
   177.4  675.35     187  675.93   206.1  677.65   215.7  677.89   273.1  677.27
   282.7  677.53   301.8     679   311.5  679.52   360.2  679.72   369.9  680.32
   379.6   681.8   389.4     684   399.1   686.6   418.5  692.47   428.3  695.78
   457.4  706.71   467.2  710.02   496.4  719.63   506.1  722.65   525.5  728.12
#Mann= 3 , 0 , 0
       0      .1       0   167.9    .045       0     187     .06       0
Bank Sta=167.9,187
XS Rating Curve= 0 ,0
Exp/Cntr=0.3,0.1

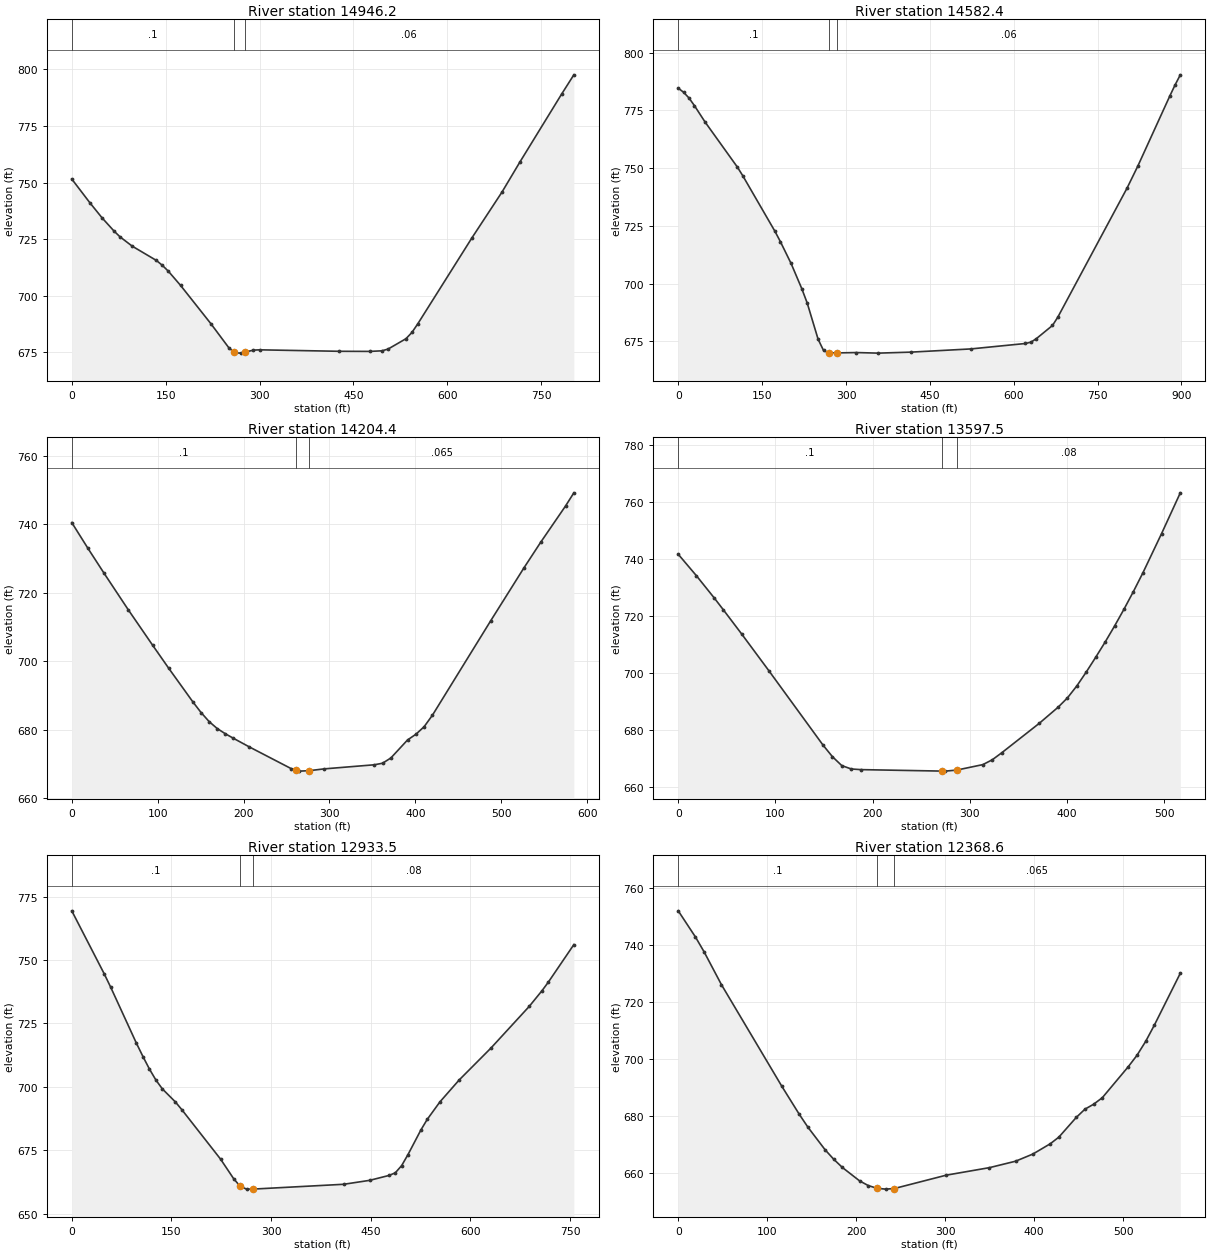
Type RM Length L Ch R = 1 ,14946.2 ,382.2,363.8,344.3
XS GIS Cut Line= 4
     1604010.571      467360.209     1603923.765      467575.053
     1603921.595       467848.49      1603999.72      468134.949
#Sta/Elev= 30
       0  751.54      29  741.03    48.3  734.42    67.6  728.53    77.2  725.97
    96.6  721.88   135.2  715.57   144.8  713.39   154.5  710.75   173.8  704.55
   222.1  687.68   251.2  676.89  259.58  675.04     261  674.76   270.8  674.63
     276  675.02   290.3  675.96   300.1  676.09     427  675.44   475.9  675.39
   495.4  675.65   505.2  676.41   533.9     681   543.5  683.79     553  687.67
   639.3  725.56   687.2  745.73   715.9  759.04   782.9  789.21   802.1  797.57
#Mann= 3 , 0 , 0
       0      .1       0  259.58    .045       0     276     .06       0
Bank Sta=259.58,276
XS Rating Curve= 0 ,0
Exp/Cntr=0.3,0.1

Type RM Length L Ch R = 1 ,14582.4 ,379.1,378,376.5
XS GIS Cut Line= 4
     1603331.317       467538.16     1603548.331      467616.285
     1603860.831      467896.233     1603962.828      468121.928
#Sta/Elev= 30
       0  784.58     9.6  782.78    19.2  780.32    28.8  777.06      48  769.91
   105.7  750.42   115.3   746.7     173  722.58   182.6  718.16   201.8  708.69
     221  697.74   230.6  691.59   250.2  675.83   259.9     671   268.8  669.98
   283.8  669.95   318.5  670.11   357.5  669.86     416  670.29   523.4  671.68
   620.9  674.03   630.7   674.6   640.4  676.12   669.3  681.84   678.8  685.42
   802.6  741.28   821.7  750.73   878.8  781.01   888.4   785.9   897.9  790.34
#Mann= 3 , 0 , 0
       0      .1       0   268.8    .045       0   283.8     .06       0
Bank Sta=268.8,283.8
XS Rating Curve= 0 ,0
Exp/Cntr=0.3,0.1

Type RM Length L Ch R = 1 ,14204.4 ,606.5,606.9,605.8
XS GIS Cut Line= 3
     1603346.508      467878.872     1603546.161      467933.126
      1603845.64       468163.16
#Sta/Elev= 30
       0   740.5    18.8  732.98    37.6  725.69    65.8  715.01      94  704.71
   112.8  697.95   141.1  688.06   150.5     685   159.9  682.35   169.3  680.32
   178.7   678.8   188.1  677.48   206.9  674.92   255.3  668.62   261.4  668.15
     265  667.87   276.4     668     294  668.53   352.1  669.72   361.8  670.18
   371.5  671.72   390.9  676.98   400.6  678.64   410.2  680.85   419.9  684.22
   487.7   711.8   526.4  727.26   545.8  734.71   574.8  745.33   584.5  749.19
#Mann= 3 , 0 , 0
       0      .1       0   261.4    .045       0   276.4    .065       0
Bank Sta=261.4,276.4
XS Rating Curve= 0 ,0
Exp/Cntr=0.3,0.1

Type RM Length L Ch R = 1 ,13597.5 ,673.8,663.9,653.1
XS GIS Cut Line= 3
     1603086.092      468254.306     1603188.088      468362.813
     1603476.717      468590.678
#Sta/Elev= 30
       0  741.57    18.6   734.1    37.2   726.2    46.5  722.08    65.2  713.68
    93.1  700.85   148.9  674.76   158.6  670.69   168.3  667.54     178  666.37
   187.6  666.14   271.6  665.62   274.7  665.61   286.6  665.98   313.4  667.89
   323.1  669.58   332.8  672.02   371.5  682.36   390.8  687.98   400.5  691.28
   410.2  695.49   419.9  700.36   429.6  705.52   439.2  710.79   448.9   716.4
   458.6   722.3   468.3  728.49     478  734.99   497.3   748.8   516.6  763.09
#Mann= 3 , 0 , 0
       0      .1       0   271.6    .045       0   286.6     .08       0
Bank Sta=271.6,286.6
XS Rating Curve= 0 ,0
Exp/Cntr=0.3,0.1

Type RM Length L Ch R = 1 ,12933.5 ,552.3,564.9,577.6
XS GIS Cut Line= 3
     1602662.914      468699.185     1603120.814      468794.671
     1603405.102      468840.244
#Sta/Elev= 30
       0  769.38    48.7  744.61    58.5  739.31    97.4  717.12   107.2  711.89
   116.9  706.99   126.7  702.63   136.4  699.15   155.9  694.04   165.7  690.96
   224.1  671.42   243.6  663.78   253.4  660.77   263.1  659.64   272.8  659.65
   409.3  661.55   448.3   663.1   477.4  665.03   486.9  666.06   496.5  668.91
   506.1  673.28   525.3  682.88   534.9   687.1   554.1  694.03   582.9  702.63
   630.9  715.26   688.5  731.68   707.7  737.86   717.3  741.26   755.7  756.05
#Mann= 3 , 0 , 0
       0      .1       0   253.4    .045       0   272.8     .08       0
Bank Sta=253.4,272.8
XS Rating Curve= 0 ,0
Exp/Cntr=0.3,0.1

Type RM Length L Ch R = 1 ,12368.6 ,589.7,589,586.9
XS GIS Cut Line= 3
     1602458.921      469059.428     1602655.537       469247.27
     1602879.928      469434.862
#Sta/Elev= 30
       0  751.83    19.4  742.63    29.1  737.43    48.6  725.91   116.5  690.26
     136  680.49   145.7  675.97   165.1  668.01   174.8  664.69   184.5  661.81
   203.9   657.1   213.6  655.46   223.4  654.51   233.1  654.21   242.8  654.41
   301.2   659.1   349.9  661.75   379.2     664   398.7  666.52   418.2  670.12
   427.9  672.46   447.4  679.35   457.2  682.26   466.9  683.98   476.7  686.27
   505.9  697.15   515.6  701.11   525.4     706   535.2  711.72   564.4  729.94
#Mann= 3 , 0 , 0
       0      .1       0   223.4    .045       0   242.8    .065       0
Bank Sta=223.4,242.8
XS Rating Curve= 0 ,0
Exp/Cntr=0.3,0.1

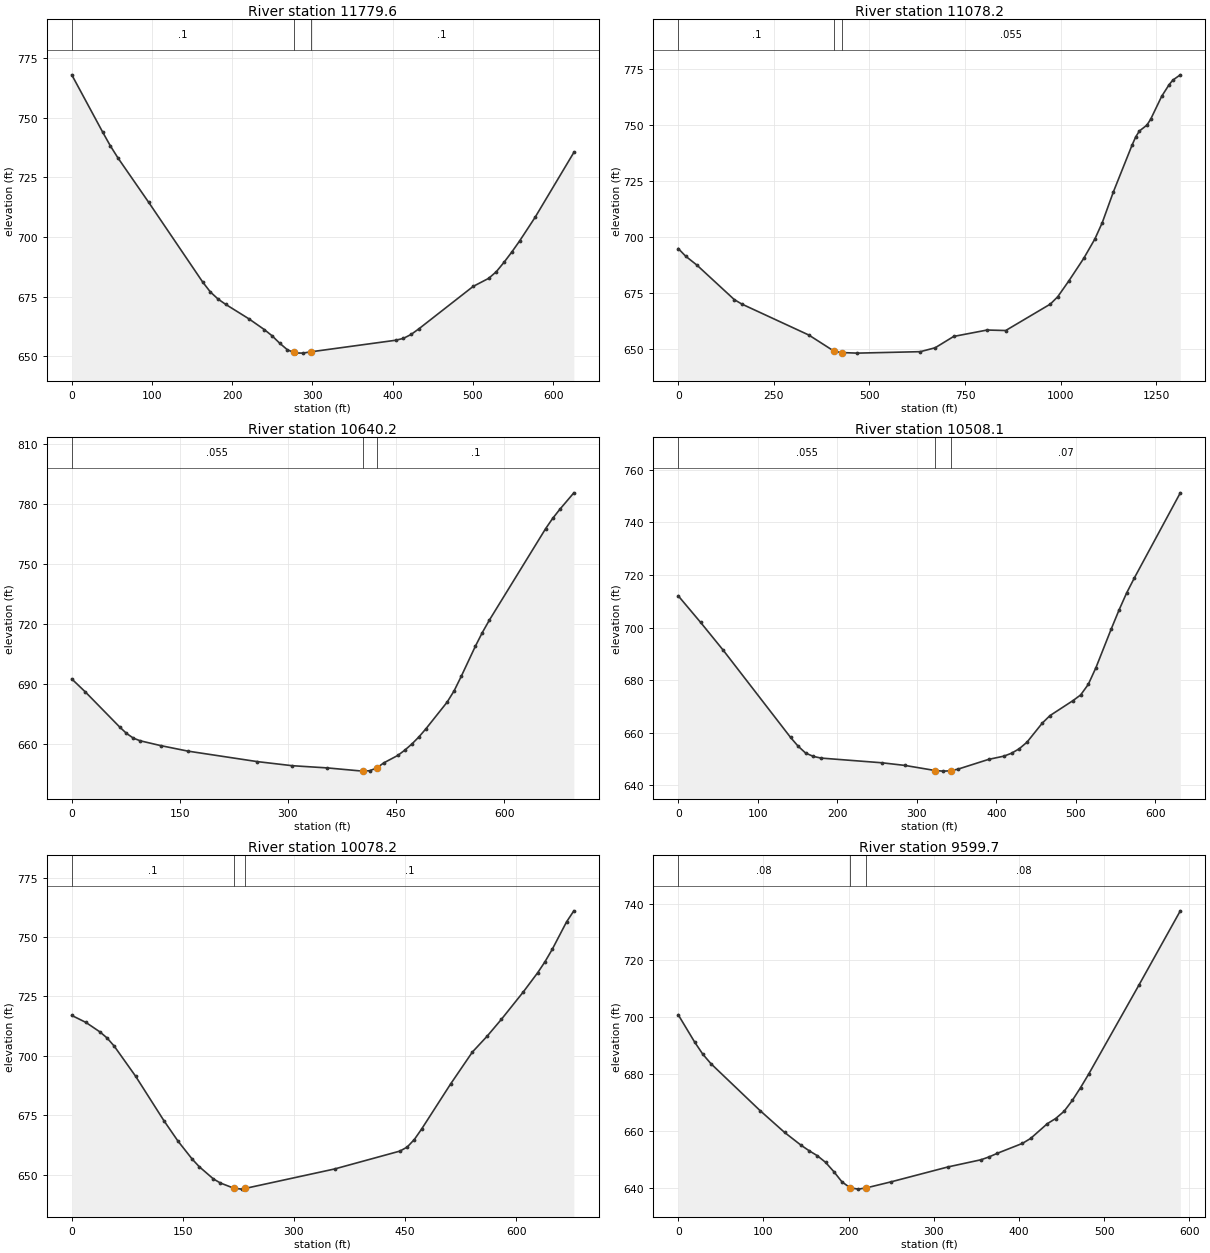
Type RM Length L Ch R = 1 ,11779.6 ,712.4,701.5,690
XS GIS Cut Line= 3
     1602044.425      469421.841     1602264.786      469607.119
     1602526.196      469821.147
#Sta/Elev= 30
       0   767.9    38.4  743.99      48  738.22    57.6  733.09      96  714.46
   163.1  681.19   172.7  677.02   182.3  674.04   191.9  671.79   220.7  665.77
   239.9  661.27   249.5   658.7   259.1  655.56   268.7  652.81  276.63  651.68
   278.3  651.48   287.9  651.39   297.6  651.92   403.7  656.78   413.4  657.57
     423  659.22   432.7  661.58   500.3  679.32   519.6  682.69   529.2  685.49
   538.9  689.47   548.5  693.73   558.2  698.35   577.5  708.25   625.8  735.41
#Mann= 3 , 0 , 0
       0      .1       0  276.63    .045       0   297.6      .1       0
Bank Sta=276.63,297.6
XS Rating Curve= 0 ,0
Exp/Cntr=0.3,0.1

Type RM Length L Ch R = 1 ,11078.2 ,414.1,438,459.7
XS GIS Cut Line= 4
     1601425.935      469914.462     1601736.265      470098.924
     1602087.828      470172.709     1602634.703      470400.574
#Sta/Elev= 30
       0  694.88    19.5  691.45    48.8  687.48   146.4  672.09   165.9   670.1
   341.5  656.23   408.3  648.92     429   648.4   467.8  648.15   632.9   648.8
   671.7  650.54   720.2  655.61   807.6  658.47   856.2  658.25   972.8  670.05
   992.2  673.34  1021.3  680.43  1060.2  690.49  1089.3  699.14  1108.7  706.47
  1137.9  720.28  1186.4  741.02  1196.1  744.75  1205.8   747.4  1225.3  750.01
    1235  752.58  1264.1  762.92  1283.6  768.13  1293.3  770.14  1312.7  772.48
#Mann= 3 , 0 , 0
       0      .1       0   408.3    .045       0     429    .055       0
Bank Sta=408.3,429
XS Rating Curve= 0 ,0
Exp/Cntr=0.3,0.1

Type RM Length L Ch R = 1 ,10640.2 ,135.8,132.1,127.1
XS GIS Cut Line= 3
     1601421.595      470116.285     1601593.036      470266.025
     1601793.344      470690.202
#Sta/Elev= 30
       0  692.69      19  686.15    66.4  668.74    75.9  665.54    85.4  663.18
    94.8  661.85   123.3  659.44   161.2  656.68     257  651.47   305.8  649.41
   354.7   648.3   403.5   646.7   413.3   646.9   423.3  648.28   432.9  650.81
   452.4  654.53   462.2  657.19     472  660.25   481.7  663.77   491.5  667.85
   520.8  681.09   530.6  686.78   540.4  693.95   559.9   708.9   569.7  715.84
   579.4     722   657.6   767.7   667.4  772.83   677.2  777.29   696.7  785.54
#Mann= 3 , 0 , 0
       0    .055       0   403.5    .045       0   423.3      .1       0
Bank Sta=403.5,423.3
XS Rating Curve= 0 ,0
Exp/Cntr=0.3,0.1

Type RM Length L Ch R = 1 ,10508.1 ,432.5,429.9,428.8
XS GIS Cut Line= 4
     1601354.321      470168.369     1601443.296      470289.897
     1601588.696      470515.591     1601697.203      470697.883
#Sta/Elev= 30
       0  712.04    28.2  701.92    56.5   691.4   141.2  658.26   150.6  654.96
   160.2   652.3   169.8  651.05   179.4  650.41   256.1  648.62   284.9  647.62
   323.2  645.67   332.8  645.45   342.4  645.57     352  646.23   390.3  649.92
   409.5  651.15   419.1  652.26   428.7  653.95   438.4  656.43   457.7   663.7
   467.3  666.53   496.2  672.22   505.9  674.39   515.5   678.4   525.2  684.81
   544.4  699.48   554.1   706.6   563.7  713.12   573.4  718.82   631.2  751.16
#Mann= 3 , 0 , 0
       0    .055       0   323.2    .045       0   342.4     .07       0
Bank Sta=323.2,342.4
XS Rating Curve= 0 ,0
Exp/Cntr=0.3,0.1

Type RM Length L Ch R = 1 ,10078.2 ,479.7,478.5,476.2
XS GIS Cut Line= 3
     1601039.651      470485.209     1601241.474      470715.244
     1601553.974      470917.067
#Sta/Elev= 30
       0  717.03    19.1  714.09    38.2  710.07    47.8  707.52    57.4   704.1
    86.1  691.53   124.3  672.86   143.4  664.22   162.6  656.65   172.1  653.46
   191.3   648.3   200.8  646.58   218.8  644.42   229.5  644.02   233.8  644.29
     355   652.5   443.1  660.01   452.9  661.69   462.6  664.88   472.4  669.26
   511.6  688.23     541  701.65   560.6   708.2   580.1  715.37   609.5  726.81
   629.1  734.96   638.9  739.54   648.7  744.75   668.2  756.38     678     761
#Mann= 3 , 0 , 0
       0      .1       0   218.8    .045       0   233.8      .1       0
Bank Sta=218.8,233.8
XS Rating Curve= 0 ,0
Exp/Cntr=0.3,0.1

Type RM Length L Ch R = 1 ,9599.7  ,666.4,677.6,685.7
XS GIS Cut Line= 3
     1600672.897      470745.626     1600930.912      471003.739
     1601085.224      471166.633
#Sta/Elev= 30
       0  700.91    19.2  691.35    28.8  687.07    38.4  683.72      96  667.26
   124.8  659.58   144.1  655.09   153.7  653.13   163.3  651.38   172.9  649.07
   182.5  645.84   192.1  642.23   201.8  640.11   211.3  639.65   220.9   640.1
   249.7   642.2   316.9  647.47   355.4  649.97     365  650.99   374.7  652.26
     404  655.72   413.7  657.48   433.2  662.64     443  664.46   452.8  666.97
   462.5   670.8   472.3  675.35     482   680.2   540.6  711.28   589.3  737.43
#Mann= 3 , 0 , 0
       0     .08       0   201.8    .045       0   220.9     .08       0
Bank Sta=201.8,220.9
XS Rating Curve= 0 ,0
Exp/Cntr=0.3,0.1

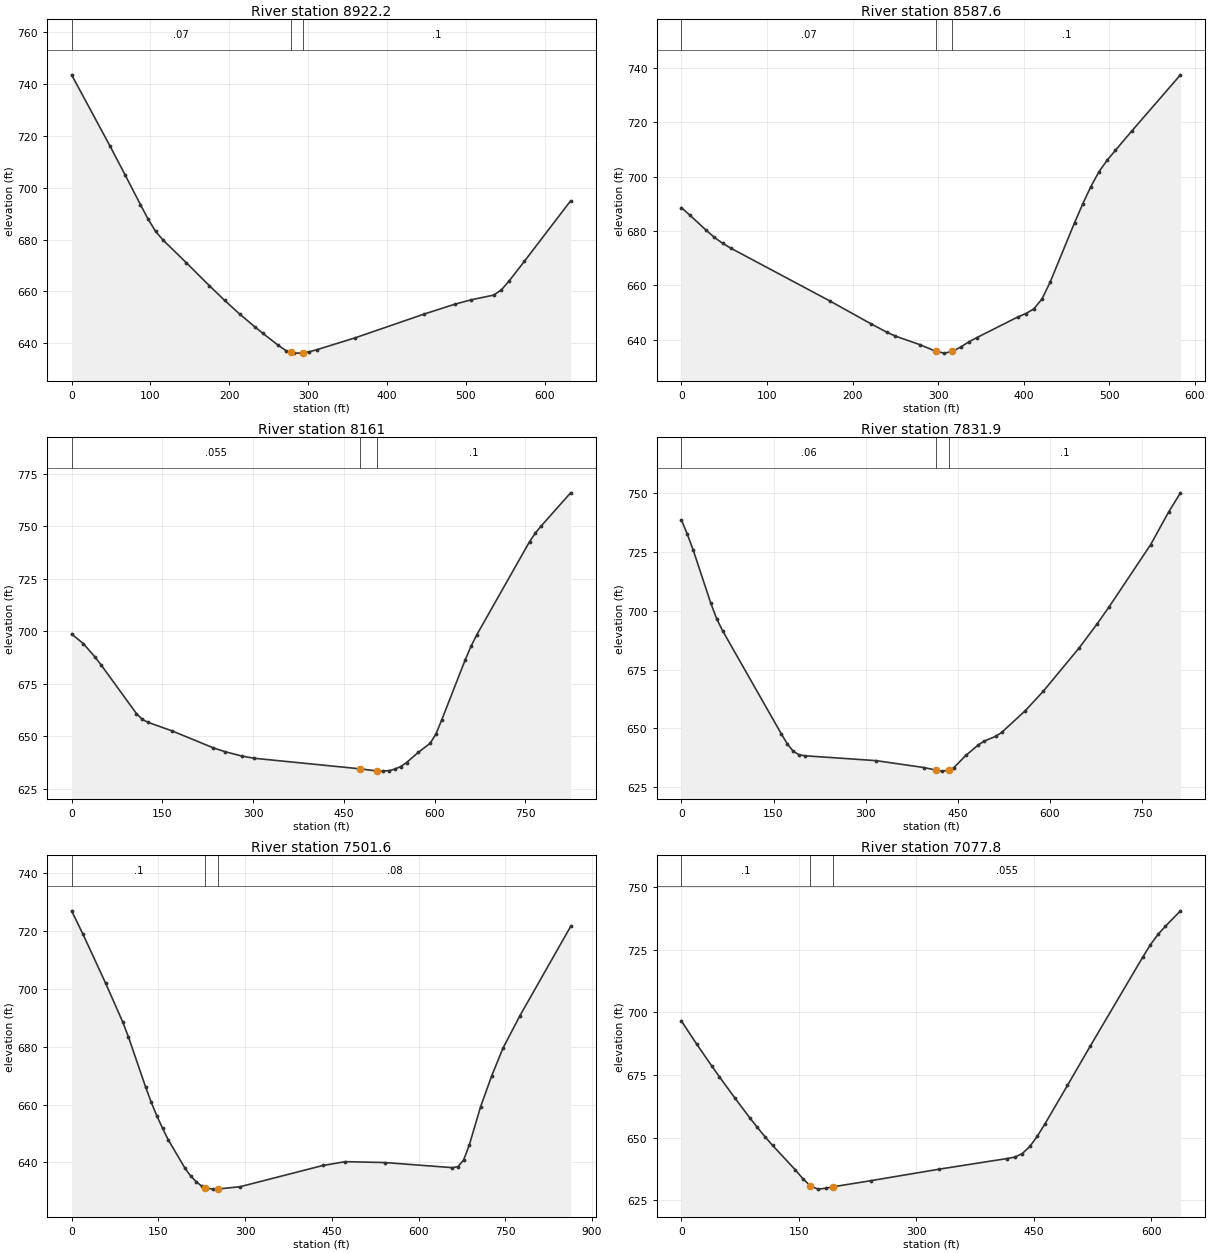
Type RM Length L Ch R = 1 ,8922.2  ,330.1,334.6,339.6
XS GIS Cut Line= 3
     1600271.421      471088.508     1600349.546      471307.692
     1600481.925      471685.296
#Sta/Elev= 30
       0  743.57    48.5   716.2    67.9  704.92    87.3  693.49      97   687.9
   106.6  683.12   116.4  679.69   145.4  671.09   174.5  662.27   193.9  656.59
   213.3  651.22   232.7  646.25   242.4  643.86     262  639.22   271.7  637.19
     278  636.55   281.5  636.19   291.2   636.2     293  636.29     301  636.69
   310.8   637.5   359.6   642.1   447.4   651.3   486.4   655.1     506  656.72
   535.2  658.58     545   660.6   554.8  664.03   574.3  671.67   632.8  694.96
#Mann= 3 , 0 , 0
       0     .07       0     278    .045       0     293      .1       0
Bank Sta=278,293
XS Rating Curve= 0 ,0
Exp/Cntr=0.3,0.1

Type RM Length L Ch R = 1 ,8587.6  ,446.9,426.7,405.7
XS GIS Cut Line= 4
     1600015.345      471170.973     1600058.748      471407.518
     1600073.939      471539.897      1600095.64       471748.23
#Sta/Elev= 30
       0  688.55     9.6  685.88    28.9  680.26    38.5  677.64    48.1  675.46
    57.7  673.67   173.2  654.31   221.2  645.93   240.5  642.71     250  641.37
   278.6  638.22   297.6  635.73   307.1   635.1   316.6   635.7   326.2  637.32
   335.7   639.2   345.2  640.81   392.8  648.34   402.3  649.61   411.8  651.34
   421.4  655.04   430.9   661.2   459.4  683.01     469  689.95   478.5  696.33
     488  701.78   497.5     706     507  709.57   526.1  716.66   583.2  737.38
#Mann= 3 , 0 , 0
       0     .07       0   297.6    .045       0   316.6      .1       0
Bank Sta=297.6,316.6
XS Rating Curve= 0 ,0
Exp/Cntr=0.3,0.1

Type RM Length L Ch R = 1 ,8161    ,326.9,329,330.9
XS GIS Cut Line= 3
     1599399.026      471411.858     1599579.147      471641.893
     1600034.876      471917.501
#Sta/Elev= 30
       0  698.71    19.5  694.13      39  687.65    48.7  684.04   107.1   660.9
   116.9   658.1   126.6  656.68   165.6  652.69   233.7  644.64   253.2  642.78
   282.4  640.61   301.8  639.63   476.2  634.62   505.2  633.56   514.9  633.51
   524.6  633.77   534.2  634.45   543.9   635.7   553.6  637.57     573  642.45
   592.4  646.68     602  651.05   611.7  657.83   650.4  686.31   660.1  692.85
   669.8  698.39     757  742.66   766.6  746.76   776.3  750.14   824.8  765.85
#Mann= 3 , 0 , 0
       0    .055       0   476.2    .045       0   505.2      .1       0
Bank Sta=476.2,505.2
XS Rating Curve= 0 ,0
Exp/Cntr=0.3,0.1

Type RM Length L Ch R = 1 ,7831.9  ,317.7,330.3,343
XS GIS Cut Line= 4
     1599210.224      471813.334     1599455.449      471921.841
     1599650.762       472067.24     1599898.158      472238.681
#Sta/Elev= 30
       0  738.67     9.6   732.6    19.2  725.81    47.9  703.19    57.5  696.57
      67  691.57   162.8  647.62   172.4  643.43     182  640.31   191.5  638.82
   201.1   638.4   316.9  636.32   394.8  633.39   414.2  632.31     424  631.86
  436.36  632.27   443.5  633.29     463  638.53   482.4  642.77   492.2  644.54
   511.6  646.66   521.4  648.31   560.2  657.64   589.3  665.87   647.6  684.26
   676.7  694.41   696.1  701.61   764.1  728.22   793.2  742.01   812.6  750.22
#Mann= 3 , 0 , 0
       0     .06       0   414.2    .045       0  436.36      .1       0
Bank Sta=414.2,436.36
XS Rating Curve= 0 ,0
Exp/Cntr=0.3,0.1

Type RM Length L Ch R = 1 ,7501.6  ,429.9,423.7,416.7
XS GIS Cut Line= 4
     1599099.546      471891.459     1599244.946      472008.647
     1599323.071       472212.64     1599450.241       472652.31
#Sta/Elev= 30
       0  727.06    19.7  718.96      59  701.93    88.5  688.54    98.3  683.41
   127.8  666.19   137.6  660.87   147.4   656.1   157.3  651.82   167.1  647.82
   196.2  637.96   205.7  635.34   215.2  633.38   224.7  631.84  230.86  631.29
   243.7  630.76   253.2  630.81   291.2  631.59   434.4  638.94   473.4  640.26
   541.5  639.96   658.4  638.19   668.1  638.54   677.8  640.82   687.6  645.98
   707.1   659.2   726.6  670.05     746  679.57   775.2  690.76   862.9  721.64
#Mann= 3 , 0 , 0
       0      .1       0  230.86    .045       0   253.2     .08       0
Bank Sta=230.86,253.2
XS Rating Curve= 0 ,0
Exp/Cntr=0.3,0.1

Type RM Length L Ch R = 1 ,7077.8  ,380,377.9,375.6
XS GIS Cut Line= 3
     1598834.789      472104.133     1599036.612      472364.549
     1599142.834      472653.597
#Sta/Elev= 30
       0  696.57    19.4  687.38    38.8  678.58    48.4  674.34    67.8  666.02
    87.2  657.94    96.9  654.11   106.6   650.4   116.3  646.94   145.4  637.14
     155  633.64   164.7  630.71   174.4  629.43     184  629.78   193.8  630.37
   242.3  632.83   329.5  637.42   416.1  641.66   425.7  642.22   435.3  643.63
     445  646.47   454.6   650.6   464.2  655.46   493.1  670.89   521.9  686.42
   589.3  722.15   598.9     727   608.6  731.15   618.2  734.45   637.4   740.6
#Mann= 3 , 0 , 0
       0      .1       0   164.7    .045       0   193.8    .055       0
Bank Sta=164.7,193.8
XS Rating Curve= 0 ,0
Exp/Cntr=0.3,0.1

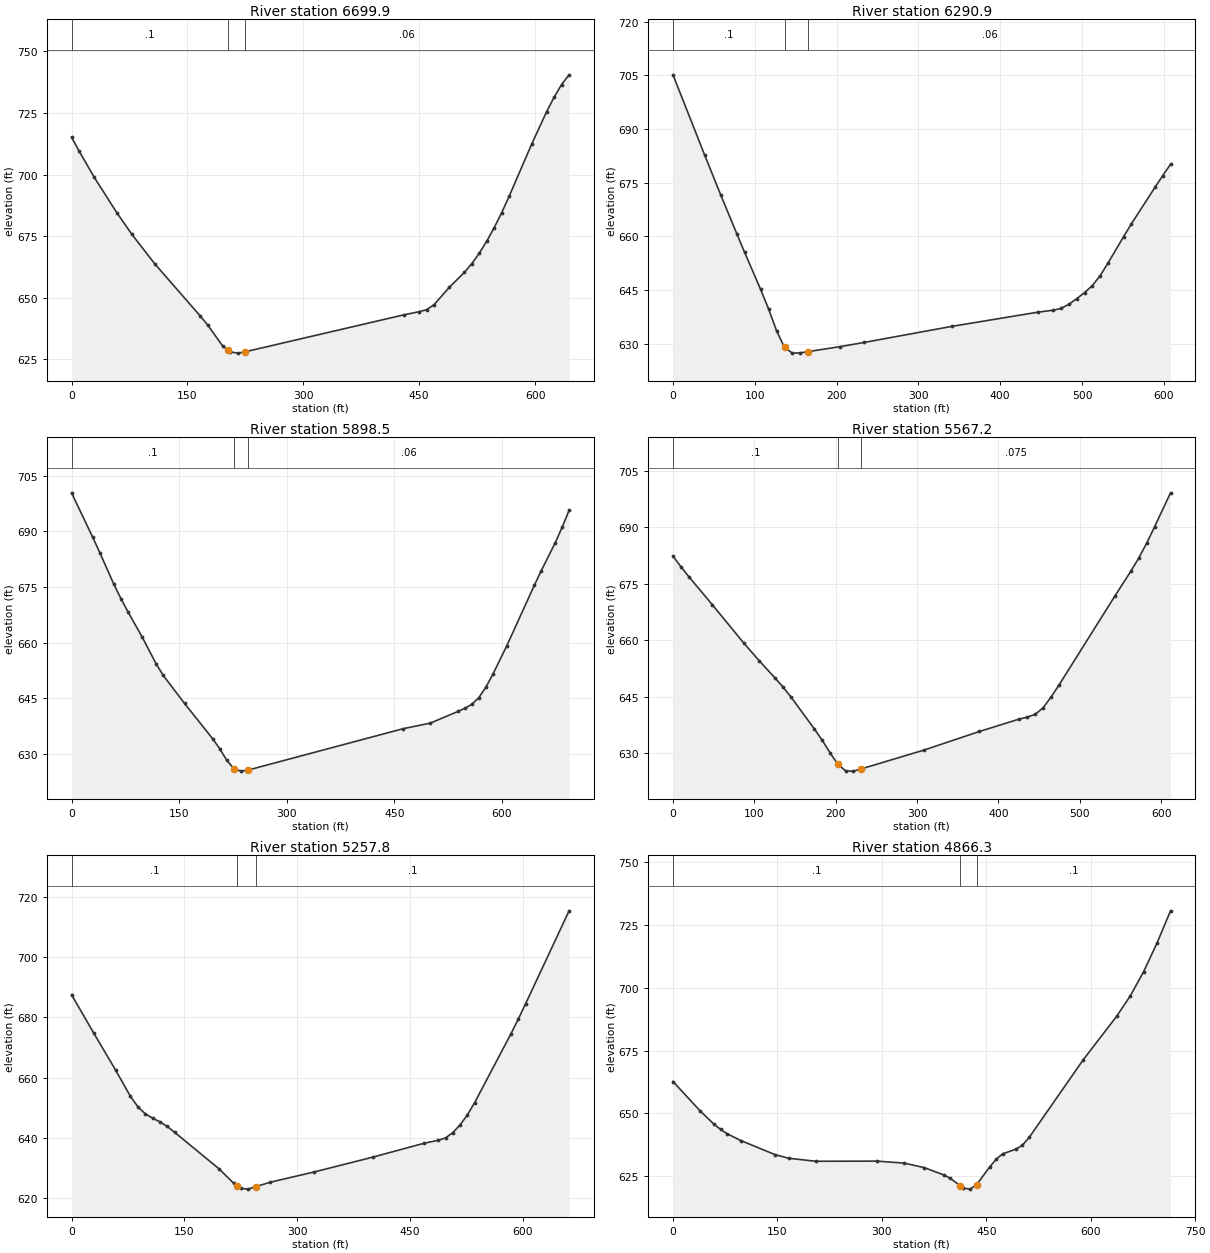
Type RM Length L Ch R = 1 ,6699.9  ,397.1,409,419.8
XS GIS Cut Line= 3
      1598526.63      472343.282      1598870.38      472704.393
      1598964.13      472815.504
#Sta/Elev= 30
       0  715.13     9.8  709.51    29.3  698.92    58.6  684.51    78.2  675.69
   107.5  663.85   166.2  642.75     176  639.03   195.5  630.47   202.4  628.79
   205.3  628.08   215.1  627.55   224.8   628.1   430.1  643.09   449.7  644.34
   459.5  645.16   469.2  647.22   488.8  654.22   508.3  660.28     518  663.84
   527.6  668.03   537.3  672.92     547  678.45   556.7  684.53   566.4  691.21
   595.5  712.32   614.9  725.52   624.6   731.4   634.2   736.5   643.9  740.44
#Mann= 3 , 0 , 0
       0      .1       0   202.4    .045       0   224.8     .06       0
Bank Sta=202.4,224.8
XS Rating Curve= 0 ,0
Exp/Cntr=0.3,0.1

Type RM Length L Ch R = 1 ,6290.9  ,392.1,392.4,392.2
XS GIS Cut Line= 3
      1598307.88      472513.421     1598394.685      472832.865
     1598453.713      473103.699
#Sta/Elev= 29
       0  705.15    38.9   682.6    58.4  671.53    77.9  660.76    87.6  655.48
   107.1  645.14   116.8  639.69   126.6  633.58   136.3  628.91     146  627.33
   155.8  627.41   165.5  627.77   204.5  629.15   233.7  630.32   340.6   634.8
   445.7  638.77   464.8  639.33   474.4  639.84     484     641   493.5  642.56
   503.1  644.25   512.6  646.21   522.2  648.99   531.8  652.52   550.9  659.94
   560.4  663.49   589.1  673.66   598.7  676.98   608.2  680.14
#Mann= 3 , 0 , 0
       0      .1       0   136.3    .045       0   165.5     .06       0
Bank Sta=136.3,165.5
XS Rating Curve= 0 ,0
Exp/Cntr=0.3,0.1

Type RM Length L Ch R = 1 ,5898.5  ,325.4,331.3,337.2
XS GIS Cut Line= 3
     1597960.658      472614.115     1598068.296      473003.004
     1598123.852      473287.726
#Sta/Elev= 30
       0  700.38    29.5  688.41    39.4  684.26      59   675.7    68.9  671.84
    78.7  668.28    98.4  661.51   118.1   654.2   127.9  651.12   157.5   643.6
   196.8  634.05   206.7  631.34   216.5  628.25   226.4  625.95   236.2  625.33
     246  625.61   461.5  636.74   500.2  638.28   538.9  641.44   548.6   642.3
   558.2  643.39   567.9  645.18   577.6  647.95   587.2   651.4   606.6  659.05
   645.2  675.46   654.9  679.41   674.3  686.91   683.9  691.09   693.6  695.63
#Mann= 3 , 0 , 0
       0      .1       0   226.4    .045       0     246     .06       0
Bank Sta=226.4,246
XS Rating Curve= 0 ,0
Exp/Cntr=0.3,0.1

Type RM Length L Ch R = 1 ,5567.2  ,310.8,309.4,307.9
XS GIS Cut Line= 3
     1597710.658      472697.449      1597714.13      473044.671
     1597700.241       473308.56
#Sta/Elev= 30
       0  682.32     9.6  679.54    19.3  676.91    48.2  669.47    86.8  659.32
   106.1  654.55   125.4  650.02     135  647.66   144.7  645.06   173.6  636.55
   183.3  633.53   192.9  630.22   202.6  627.14   212.2  625.38   221.8  625.32
   231.5  625.92   308.7  630.92   376.6  635.83   425.5  639.12   435.3  639.63
   445.1  640.35   454.9  642.13   464.7  644.97   474.5  648.18     543   671.7
   562.6  678.28   572.3  681.75   582.1  685.72   591.9  690.09   611.5   699.1
#Mann= 3 , 0 , 0
       0      .1       0   202.6    .045       0   231.5    .075       0
Bank Sta=202.6,231.5
XS Rating Curve= 0 ,0
Exp/Cntr=0.3,0.1

Type RM Length L Ch R = 1 ,5257.8  ,395.9,391.6,386.6
XS GIS Cut Line= 3
     1597387.741      472669.671     1597415.519      473030.782
     1597436.352      473329.393
#Sta/Elev= 30
       0  687.56    29.4  674.85    58.7  662.45    78.3  653.78    88.1  650.33
    97.9     648   107.7  646.52   117.5  645.31   127.2  643.75     137  641.84
   195.8  629.74   215.4  624.93   220.5  623.98   225.1  623.19   234.9  622.93
   244.7  623.74   264.3  625.23     323  628.66   400.8  633.58   468.4  638.16
   487.7  639.18   497.4  639.96     507  641.74   516.7  644.32   526.3  647.61
     536   651.7   584.3   674.6   593.9  679.41   603.6   684.5   661.5  715.44
#Mann= 3 , 0 , 0
       0      .1       0   220.5    .045       0   244.7      .1       0
Bank Sta=220.5,244.7
XS Rating Curve= 0 ,0
Exp/Cntr=0.3,0.1

Type RM Length L Ch R = 1 ,4866.3  ,296.6,285.4,274.5
XS GIS Cut Line= 4
     1597005.796       472746.06     1597106.491      473082.865
     1597144.685      473218.282     1597231.491      473423.143
#Sta/Elev= 30
       0  662.69    39.1  650.95    58.6  645.76    68.4  643.61    78.1  641.83
    97.6  639.17   146.5  633.58     166  632.14   205.1  630.93     293  630.99
     332  630.21   360.9   628.4   389.1  625.49   398.4  624.15  412.92  621.08
   417.2  620.24   426.6  619.84     436  621.57   454.7  628.59   464.1  631.71
   473.5  633.89   492.2  635.71   501.9  637.32   511.6   640.4     589  671.24
   637.3  688.65   656.7   696.7     676   706.4   695.4  717.88   714.7  730.65
#Mann= 3 , 0 , 0
       0      .1       0  412.92    .045       0     436      .1       0
Bank Sta=412.92,436
XS Rating Curve= 0 ,0
Exp/Cntr=0.3,0.1

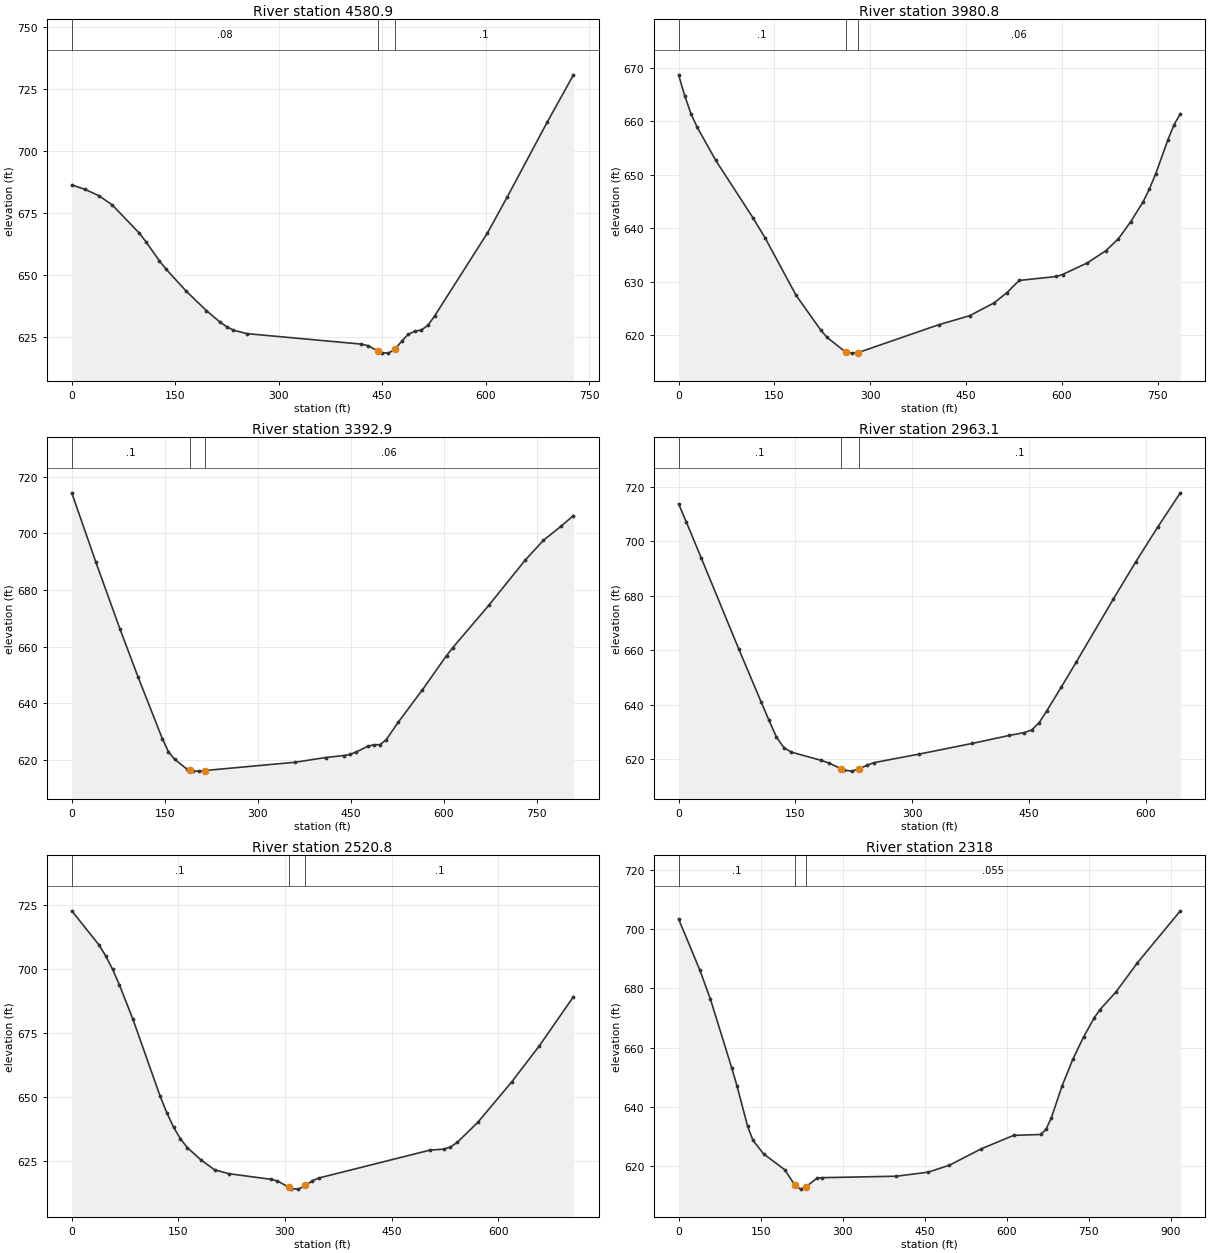
Type RM Length L Ch R = 1 ,4580.9  ,601.3,600.1,601
XS GIS Cut Line= 3
     1596606.476      472995.676     1596923.151      473327.955
     1597103.019       473527.31
#Sta/Elev= 30
       0  686.32    19.5  684.51    39.1  682.04    58.6  678.32    97.7  667.02
   107.4  663.56     127  655.85   136.7   652.5     166  643.61   195.3  635.78
   214.9  631.21   224.6  629.33   234.4  627.94   253.9  626.55     420  622.33
   429.7  621.69  443.83  619.61   449.2   618.9     459  618.71   468.6   620.2
   478.2  623.46   487.8  626.22   497.4  627.53     507  627.98   516.6  629.98
   526.1  633.63   602.8  667.03   631.6  681.57   689.2  711.46   727.5  730.59
#Mann= 3 , 0 , 0
       0     .08       0  443.83    .045       0   468.6      .1       0
Bank Sta=443.83,468.6
XS Rating Curve= 0 ,0
Exp/Cntr=0.3,0.1

Type RM Length L Ch R = 1 ,3980.8  ,589.2,587.9,583.5
XS GIS Cut Line= 3
      1596276.63      473530.782     1596475.816      473714.756
     1596804.408      474110.643
#Sta/Elev= 30
       0  668.65     9.7   664.7    19.4  661.38      29   658.9    58.1  652.69
   116.2     642   135.6  638.18     184  627.48   222.7  620.98   232.4  619.63
   261.5   616.9   271.2  616.69   280.9  616.78     407  621.98   455.6  623.67
   494.4   626.1   513.8  627.96   533.2  630.26   591.5     631   601.2  631.37
     640  633.54   669.2  635.83   688.6  638.04     708  641.25   727.4  644.96
   737.1  647.33   746.8  650.09   766.2  656.54   775.9  659.36   785.6  661.39
#Mann= 3 , 0 , 0
       0      .1       0   261.5    .045       0   280.9     .06       0
Bank Sta=261.5,280.9
XS Rating Curve= 0 ,0
Exp/Cntr=0.3,0.1

Type RM Length L Ch R = 1 ,3392.9  ,421.2,429.8,438.1
XS GIS Cut Line= 2
     1595912.046       473996.06     1596540.519      474506.476
#Sta/Elev= 30
       0  714.37      39   689.8      78  666.12   107.3  649.11   146.3   627.4
   156.1  622.85   165.8  620.21   185.3  616.83  190.17   616.4   195.1  616.02
   204.8     616   214.6  616.21   360.9  619.15   409.7  620.81     439  621.51
   448.7  621.88   458.5  622.71     478  624.82   487.7   625.3   497.5  625.37
   507.2  627.04   526.8  633.28   565.8  644.74   604.8  656.84   614.5  659.57
   673.1  674.65   731.6  690.56   760.9  697.56   790.1  702.66   809.6  706.35
#Mann= 3 , 0 , 0
       0      .1       0  190.17    .045       0   214.6     .06       0
Bank Sta=190.17,214.6
XS Rating Curve= 0 ,0
Exp/Cntr=0.3,0.1

Type RM Length L Ch R = 1 ,2963.1  ,436.1,442.3,448.6
XS GIS Cut Line= 3
     1595675.935      474249.532     1595880.796      474610.643
     1595967.602      474822.449
#Sta/Elev= 30
       0  713.78     9.7  707.29      29  693.99    77.2  660.54   106.2   640.9
   115.9  634.42   125.5  628.25   135.2  624.26   144.8  622.65   183.4  619.59
   193.1  618.65   208.9  616.48   212.3  616.08   222.1  615.67   231.7  616.42
   241.4  617.79     251  618.79     309  621.94   376.6  625.82   424.7  628.79
   443.8  629.82   453.3  630.78   462.9  633.48   472.4  637.68   491.5  646.62
   510.6  655.77   558.2   678.9   586.8  692.47   615.5  705.46   644.1  717.84
#Mann= 3 , 0 , 0
       0      .1       0   208.9    .045       0   231.7      .1       0
Bank Sta=208.9,231.7
XS Rating Curve= 0 ,0
Exp/Cntr=0.3,0.1

Type RM Length L Ch R = 1 ,2520.8  ,190.9,202.9,214.4
XS GIS Cut Line= 4
     1595391.213      474346.754     1595380.796      474537.726
     1595436.352      474766.893      1595526.63      475030.782
#Sta/Elev= 30
       0  722.83    38.2  709.56    47.8  705.23    57.4  700.01    66.9  694.04
    86.1  680.49   124.3   650.5   133.9  643.91   143.4   638.3     153   633.8
   162.6   630.4   181.7  625.61   201.1  621.71   220.7  620.23   279.7  618.03
   289.5  617.38  305.17  614.96   309.2  614.38     319  614.18   328.8  615.61
   338.6  617.46   348.5  618.58     504  629.41   523.2  629.78   532.8  630.62
   542.5  632.45   571.3  640.24   619.4  656.15   657.9  670.11     706  689.32
#Mann= 3 , 0 , 0
       0      .1       0  305.17    .045       0   328.8      .1       0
Bank Sta=305.17,328.8
XS Rating Curve= 0 ,0
Exp/Cntr=0.3,0.1

Type RM Length L Ch R = 1 ,2318    ,361.2,364.1,366.5
XS GIS Cut Line= 3
     1595311.352      474346.754     1595165.519      474860.643
      1595057.88      475228.699
#Sta/Elev= 30
       0  703.39    38.8  686.21    58.3  676.33    97.1  653.27   106.8  647.16
   126.3   633.5     136  628.84   155.4  624.26   194.2  618.89   213.1   613.6
   223.4  612.37   233.1  613.17   252.5  615.97   262.2  616.23   398.2  616.72
   456.5  618.09   495.3  620.43   553.8  625.98   612.8  630.49     662  630.78
   671.8  632.48   681.7   636.4   701.3  647.15     721  656.14   740.7  663.68
   760.3  670.12   770.2  672.79   799.7  678.78     839  688.61   917.6  706.15
#Mann= 3 , 0 , 0
       0      .1       0   213.1    .045       0   233.1    .055       0
Bank Sta=213.1,233.1
XS Rating Curve= 0 ,0
Exp/Cntr=0.3,0.1