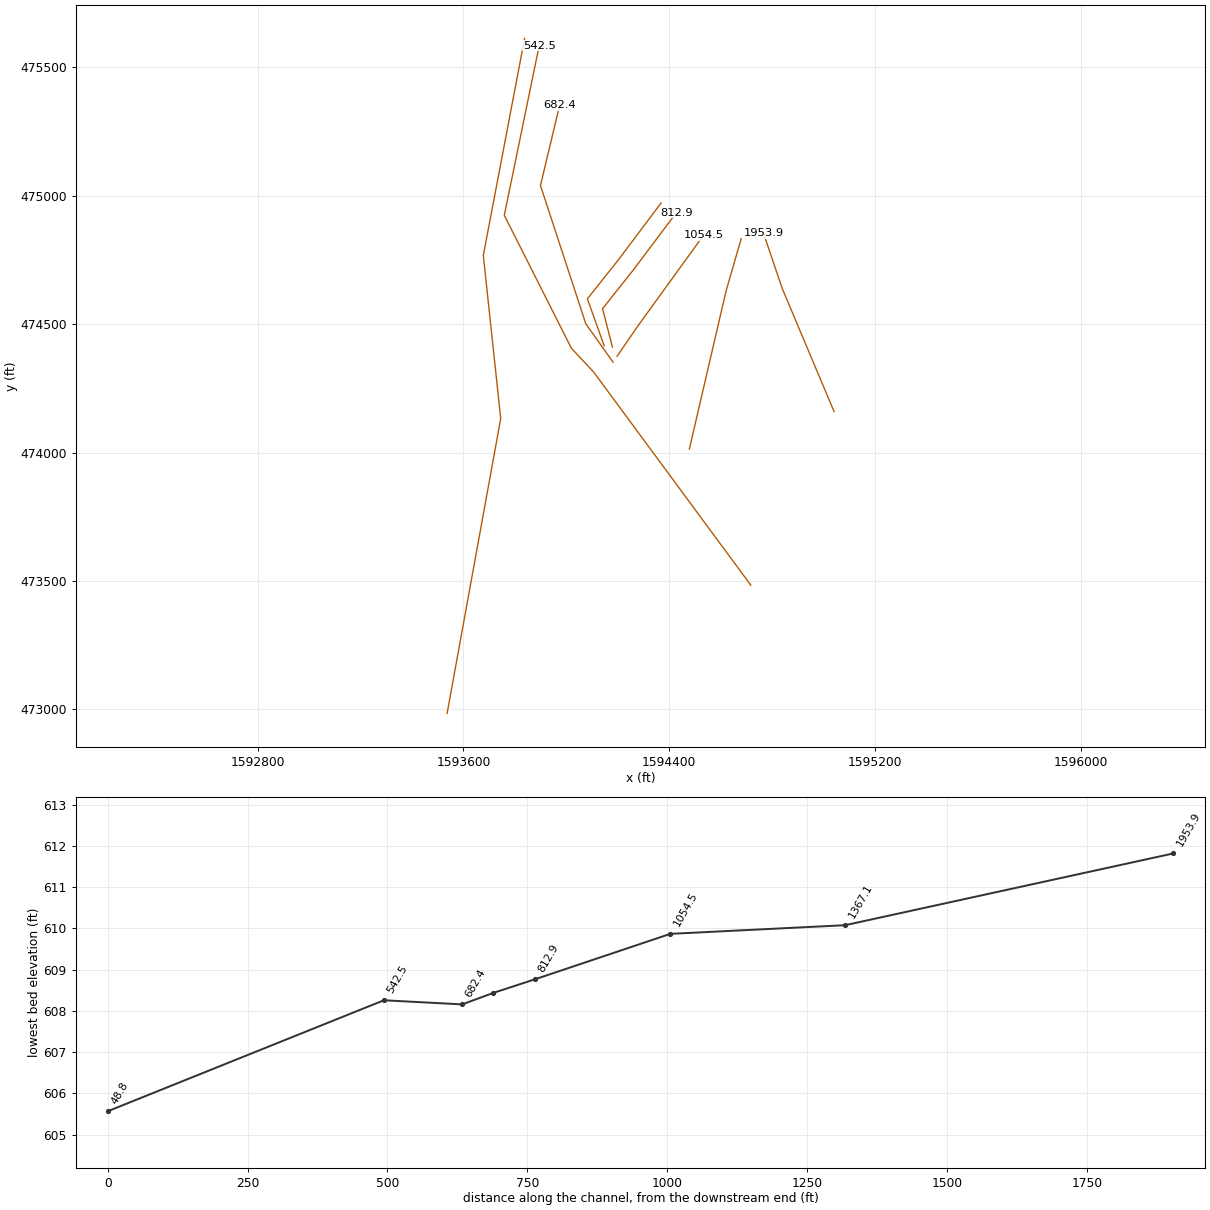
HEC-RAS study BowenCr.prj: BowenCr

--- BowenCr.g01 (geometry) --- (continued)

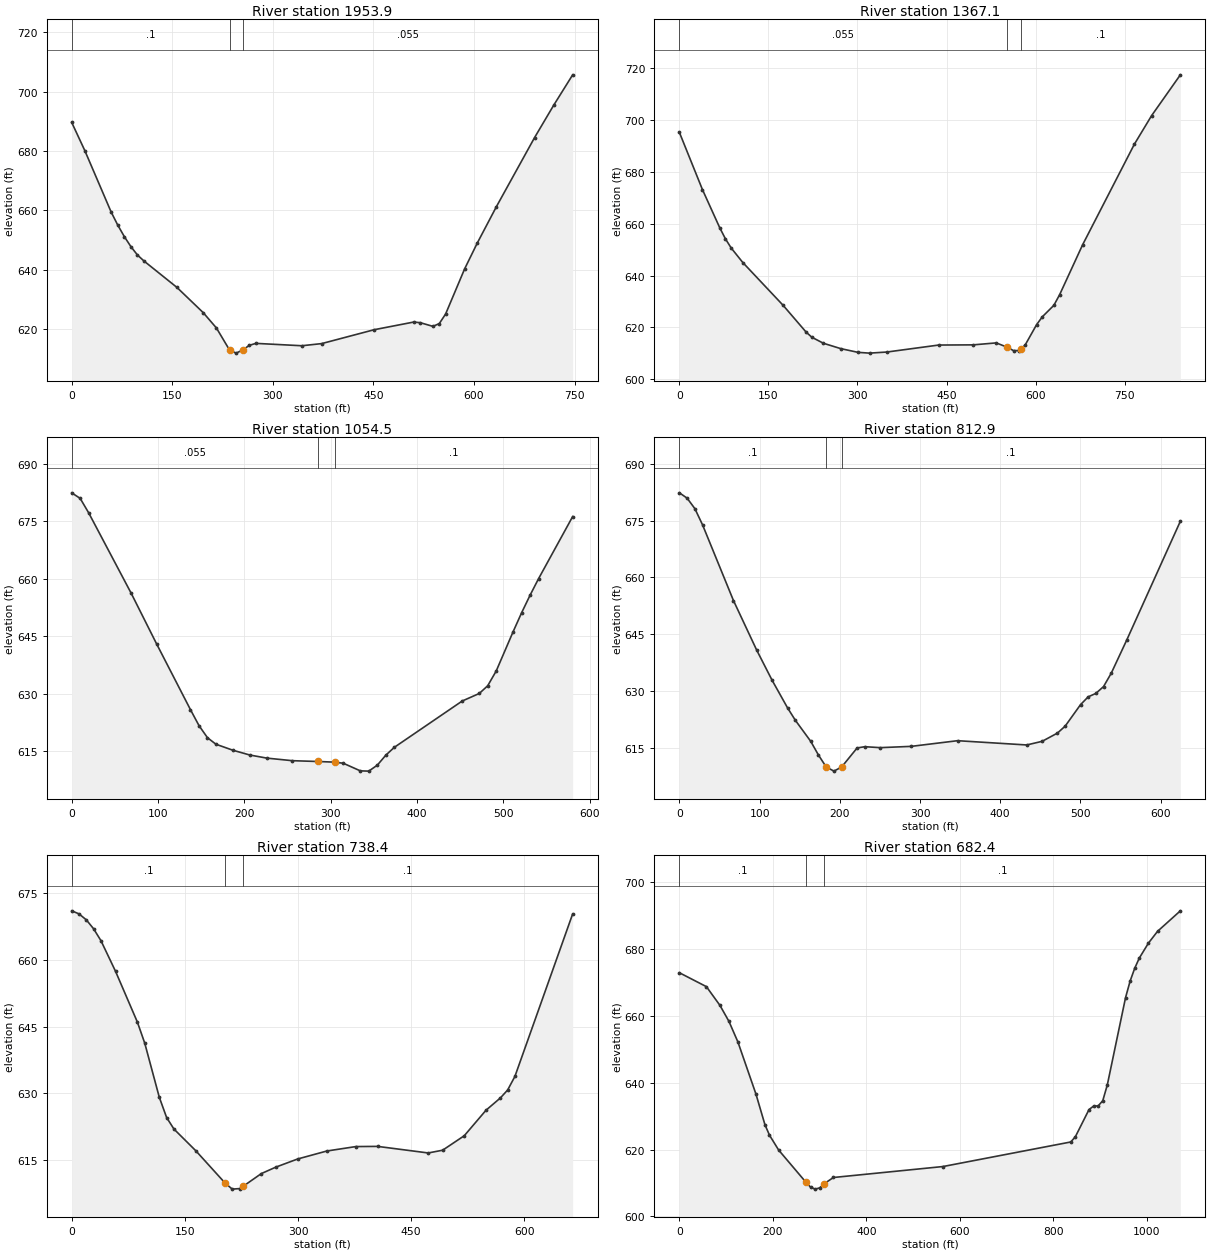
Type RM Length L Ch R = 1 ,1953.9  ,610.3,586.8,574.3
XS GIS Cut Line= 3
     1595040.519      474159.254      1594839.13      474638.421
     1594766.213      474853.699
#Sta/Elev= 30
       0  689.64    19.6   680.1    58.8  659.42    68.6  655.03    78.5  651.11
    88.3  647.73    98.1   644.9   107.9  642.87   156.9  633.99   196.1  625.48
   215.8  620.31   235.4  612.86   245.2  611.82     255  612.87   264.8  614.44
   274.6  615.11   343.2  614.31   372.7  615.03   451.1  619.72     510   622.3
   519.8  622.09   538.7  620.85   548.2  621.79   557.6  625.01   586.1   640.3
     605  649.02   633.4  661.24   690.2  684.49   718.6  695.36   747.1  705.69
#Mann= 3 , 0 , 0
       0      .1       0   235.4    .045       0     255    .055       0
Bank Sta=235.4,255
XS Rating Curve= 0 ,0
Exp/Cntr=0.3,0.1

Type RM Length L Ch R = 1 ,1367.1  ,315.6,312.5,303.4
XS GIS Cut Line= 3
     1594478.019      474013.421      1594620.38      474628.004
     1594679.408      474832.865
#Sta/Elev= 30
       0  695.27    38.8  673.21    67.9   658.5    77.6  654.17    87.4  650.61
   106.8  645.06   174.7  628.54   213.5  618.19   223.2   616.2   242.6  613.89
   271.8  611.82   300.9  610.38   320.3  610.08   349.4   610.5   436.8   613.2
     495  613.27   533.8  614.03   551.7  612.41   562.9  611.05   572.6  611.07
  574.99  611.63   582.3  613.13   601.7  621.04   611.4   624.1   630.9  628.54
   640.6  632.64   679.3   651.9   766.5  690.73   795.6  701.78     844  717.51
#Mann= 3 , 0 , 0
       0    .055       0   551.7    .045       0  574.99      .1       0
Bank Sta=551.7,574.99
XS Rating Curve= 0 ,0
Exp/Cntr=0.3,0.1

Type RM Length L Ch R = 1 ,1054.5  ,242.2,241.7,237.1
XS GIS Cut Line= 3
     1594196.769      474374.532     1594280.102       474496.06
     1594533.574      474846.754
#Sta/Elev= 30
       0  682.39     9.8  680.94    19.6  677.19    68.8  656.25    98.2  643.07
   137.5  625.89   147.4  621.73   157.2  618.58     167  616.88   186.7  615.31
   206.4  614.06     226  613.26   255.5  612.59     285  612.38   304.7  612.21
   314.5  611.92   334.2  609.94     344  609.87   353.9  611.43   363.7  614.02
   373.5  616.06   452.2  628.14   471.9   630.1   481.7  632.11   491.6  635.98
   511.2  646.23   521.1  651.19   530.9  655.77   540.7  660.06   580.1  676.21
#Mann= 3 , 0 , 0
       0    .055       0     285    .045       0   304.7      .1       0
Bank Sta=285,304.7
XS Rating Curve= 0 ,0
Exp/Cntr=0.3,0.1

Type RM Length L Ch R = 1 ,812.9   ,70.8,74.5,73.4
XS GIS Cut Line= 4
     1594178.829       474410.99     1594140.634      474560.296
     1594260.426      474711.337     1594427.093       474933.56
#Sta/Elev= 30
       0  682.38     9.6  680.97    19.3  678.19    28.9  673.89    67.4  653.89
    96.3  640.81   115.6   632.8   134.8  625.52   144.5  622.24   163.8  616.64
   173.4  613.02     183  609.88   192.7  608.77   202.3  609.86   221.6   614.9
   231.2  615.23   250.5  614.98   289.1  615.32   346.9  616.82   433.1  615.69
   452.3  616.65   471.4  618.83     481  620.66   500.2  626.35   509.7  628.41
   519.3  629.33   528.9  631.13   538.5  634.67   557.6  643.34   624.7  674.87
#Mann= 3 , 0 , 0
       0      .1       0     183    .045       0   202.3      .1       0
Bank Sta=183,202.3
XS Rating Curve= 0 ,0
Exp/Cntr=0.3,0.1

Type RM Length L Ch R = 1 ,738.4   ,39.3,56,79.6
XS GIS Cut Line= 4
     1594146.711      474416.199     1594081.607       474598.49
     1594201.398      474749.532     1594368.065      474971.754
#Sta/Elev= 30
       0  671.09     9.7   670.4    19.4  669.05      29  667.05    38.7  664.39
    58.1  657.47    87.1  646.02    96.8  641.31   116.1  629.12   125.8  624.56
   135.5  621.97   164.5  617.08   203.2  609.83   212.8  608.44   222.5  608.56
  227.54  609.11   251.4  611.94   270.7   613.4   299.6  615.23   338.2  617.02
   376.7  618.02   405.5  618.06   472.6  616.58   491.7   617.2   520.4  620.46
   549.2   626.2   568.3  628.97   577.9  630.76   587.5   633.8   664.1   670.4
#Mann= 3 , 0 , 0
       0      .1       0   203.2    .045       0  227.54      .1       0
Bank Sta=203.2,227.54
XS Rating Curve= 0 ,0
Exp/Cntr=0.3,0.1

Type RM Length L Ch R = 1 ,682.4   ,139.1,139.9,139.3
XS GIS Cut Line= 4
     1594181.433      474351.962      1594075.53      474501.268
     1593899.315      475039.897     1593973.968      475353.699
#Sta/Elev= 30
       0  672.91    57.8  668.75    86.7  663.16     106  658.37   125.2   652.2
   163.8  636.62     183  627.48   192.8   624.3   212.4  619.86     271  610.19
   280.8  608.74   290.5  608.16   300.3  608.53   310.1  609.79   329.6  611.64
   564.1  614.92   837.7  622.27   847.5  623.83   876.8  631.98   886.6  633.01
   896.4  633.07   906.2  634.62   915.9  639.33     955  665.49   964.8  670.44
   974.6  674.26   984.4   677.3  1003.9  681.77  1023.5  685.31  1072.3  691.44
#Mann= 3 , 0 , 0
       0      .1       0     271    .045       0   310.1      .1       0
Bank Sta=271,310.1
XS Rating Curve= 0 ,0
Exp/Cntr=0.3,0.1

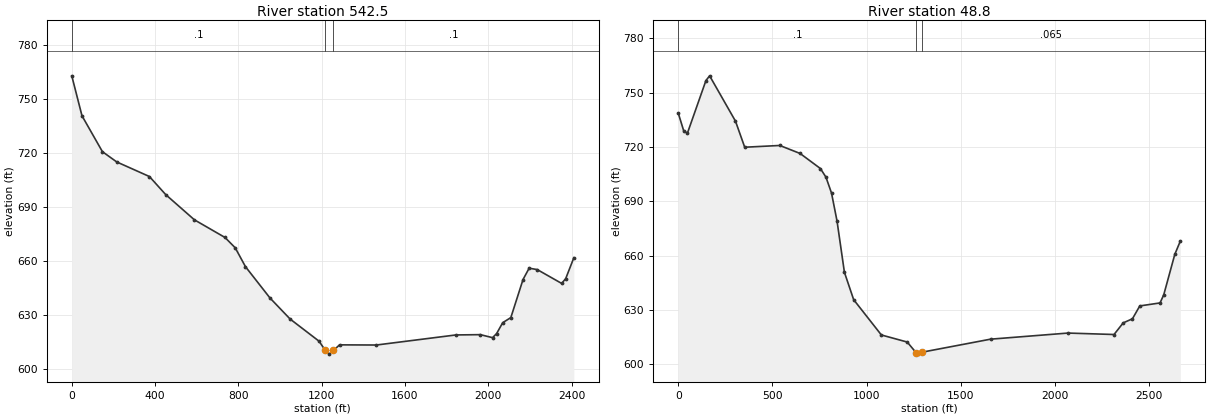
Type RM Length L Ch R = 1 ,542.5   ,496.6,493.6,486.8
XS GIS Cut Line= 5
     1594717.023      473483.039     1594106.348      474312.946
     1594019.107       474406.65      1593758.69      474924.011
     1593894.107      475583.733
#Sta/Elev= 30
       0  762.88    49.1  740.67   147.2  720.74   215.9  715.04   372.9  706.93
   451.4  696.86   588.8  682.89     736  673.06     785  667.32   834.1  656.86
   951.9  639.45  1048.7  627.74  1187.8  615.42  1217.3  610.37  1236.9  608.26
  1256.6  610.31    1286  613.41  1462.7  613.32    1845  618.92  1962.1  619.08
  2020.7  617.41  2040.2  619.67  2069.5  625.73  2108.5  628.56  2167.1  649.72
  2196.4     656  2235.4  655.23  2352.5  647.55    2372  650.21  2411.1  661.81
#Mann= 3 , 0 , 0
       0      .1       0  1217.3    .045       0  1256.6      .1       0
Bank Sta=1217.3,1256.6
XS Rating Curve= 0 ,0
Exp/Cntr=0.3,0.1

Type RM Length L Ch R = 1 ,48.8    ,56.3,48.8,41.7
XS GIS Cut Line= 4
     1593536.468      472983.907     1593744.801      474132.344
     1593677.093      474767.761     1593837.683      475613.247
#Sta/Elev= 30
       0  738.77    29.4  728.84      49  727.72   147.1  756.73   166.7  759.34
   304.1  734.29   353.1  719.89   539.4  720.86   647.3  716.44   755.2  708.11
   784.7  703.33   814.1  694.59   843.5  679.08   882.7  650.78   931.8  635.65
  1078.9  616.16  1216.3  612.24  1265.5  606.11  1275.3  605.57    1295  606.64
  1658.7  613.83  2070.2  617.21  2314.7  616.41  2363.6  622.85  2412.5  625.09
  2451.6   632.2  2559.2  633.86  2578.8  638.34  2637.5  660.69  2666.8  668.01
#Mann= 3 , 0 , 0
       0      .1       0  1265.5    .045       0    1295    .065       0
Bank Sta=1265.5,1295
XS Rating Curve= 0 ,0
Exp/Cntr=0.3,0.1

Chan Stop Cuts=-1
Use User Specified Reach Order=0
Composite Channel Slope=5